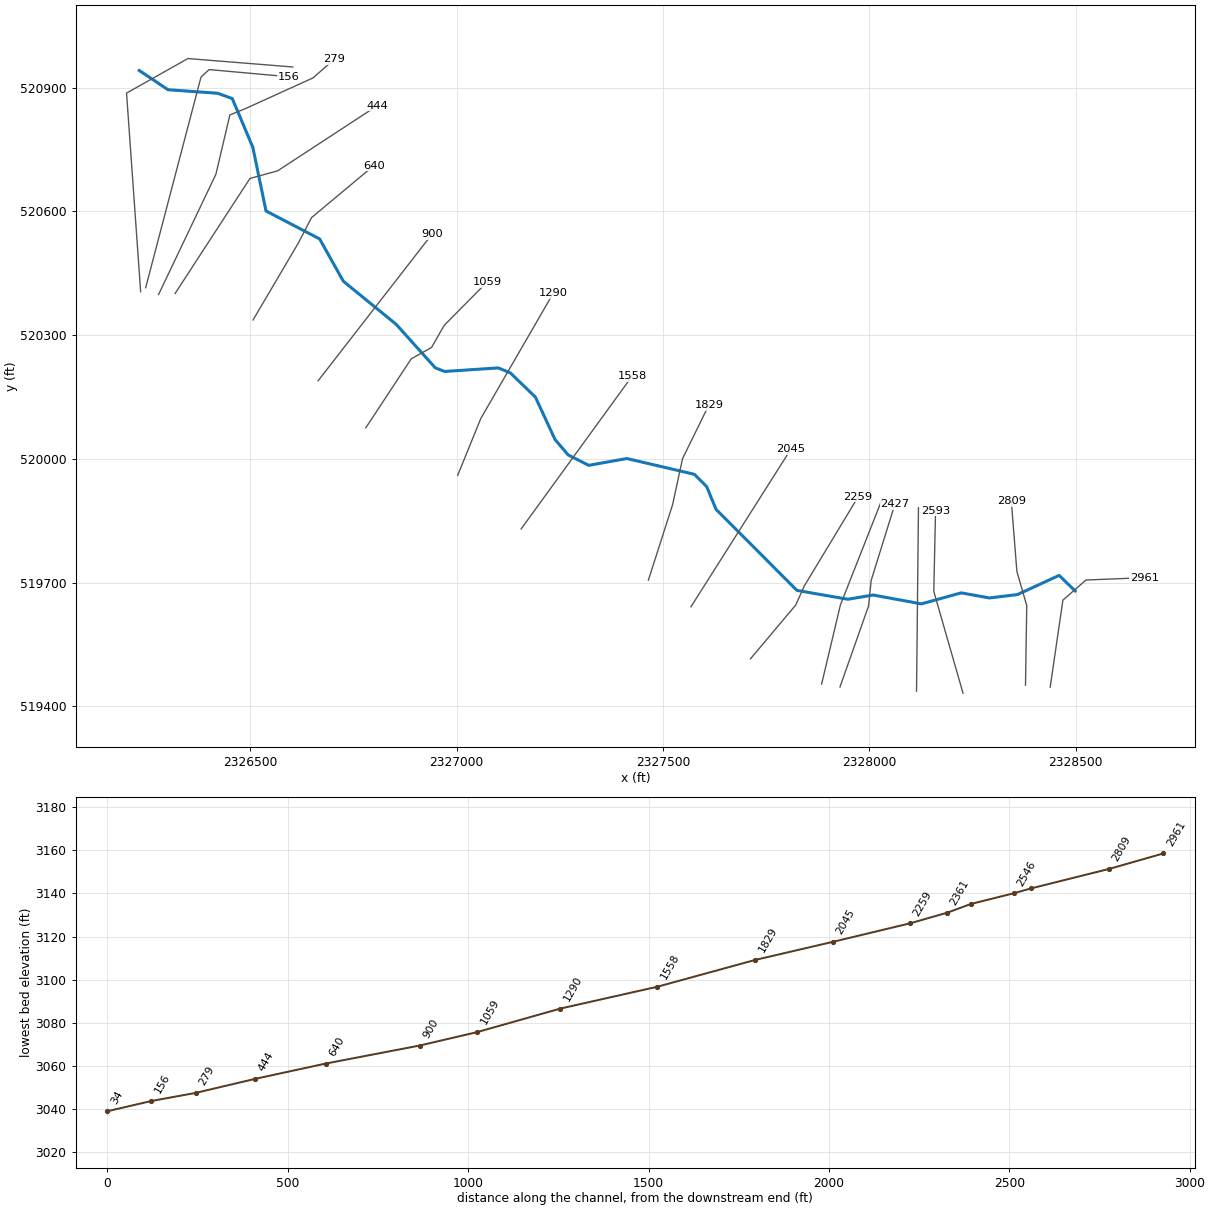
--- TCKRFRK.prj (project) ---

Proj Title=TCKRFRK
Current Plan=p01
Default Exp/Contr=0,0
English Units
Geom File=g01
Flow File=f01
Plan File=p01
BEGIN DESCRIPTION:
----------MODEL BY WOOD PLC 2021----------
Stream Name: Tacker Fork
Flood Zone: Enhanced Approximate
Pocahontas County, WV
HEC-RAS Version: RAS 6.1
Vertical Datum: NAVD88
Projection: NAD 1983 StatePlane West Virginia S FIPS 4702 (US Feet)
Terrain: 1-meter LIDAR (FEMA Region III 3DEP collected 2016-2018)
Land Use: 2019 NLCD
Hydrologic Method:
WV SIR2010-5033 regression equations
Model Notes:
Normal depth tie in to North Fork
END DESCRIPTION:
DSS Export Rating Curves= 0
DSS Export Rating Curve Sorted= 0
DSS Export Volume Flow Curves= 0
DXF OffsetX= 0
DXF OffsetY= 0
DXF ScaleX= 0
DXF ScaleY= 0

--- TCKRFRK.p01 (plan) ---

Plan Title=Floodplain
Program Version=6.10
Short Identifier=Floodplain
Geom File=g01
Flow File=f01
Subcritical Flow
K Sum by GR= 0
Std Step Tol= 0.01
Critical Tol= 0.01
Num of Std Step Trials= 20
Max Error Tol= 0.3
Flow Tol Ratio= 0.001
Split Flow NTrial= 30
Split Flow Tol= 0.02
Split Flow Ratio= 0.02
Log Output Level= 0
Friction Slope Method= 1
Unsteady Friction Slope Method= 2
Unsteady Bridges Friction Slope Method= 1
Parabolic Critical Depth
Global Vel Dist= 0 , 0 , 0
Global Log Level= 0
CheckData=True
Encroach Param=-1 ,0,0, 0
Mapping Interval=1HOUR
Computation Time Step Use Courant=        0
Computation Time Step Use Time Series=    0
Computation Time Step Count To Double=0
Computation Time Step Max Doubling=0
Computation Time Step Max Halving=0
Computation Time Step Residence Courant=0
Run HTab= 0
Run UNet= 0
Run Sediment= 0
Run PostProcess= 0
Run WQNet= 0
Run RASMapper=-1
UNET Theta= 0
UNET Theta Warmup= 0
UNET ZTol= 0
UNET ZSATol= 0
UNET MxIter= 0
UNET Max Iter WO Improvement= 0
UNET MaxInSteps= 0
UNET DtIC= 0
UNET DtMin= 0
UNET MaxCRTS= 0
UNET WFStab= 0
UNET SFStab= 0
UNET WFX= 1
UNET SFX= 1
UNET Gravity=32.174
UNET 1D Methodology=Finite Difference
UNET DSS MLevel= 1
UNET Pardiso=0
UNET DZMax Abort= 0
UNET Use Existing IB Tables= 0
UNET Froude Reduction=False
UNET Froude Limit= 0
UNET Froude Power= 0
UNET D1 Cores= 0
UNET WindReference=Eulerian
UNET WindDragFormulation=Hsu (1988)
UNET D2 Coriolis=0
UNET D2 Cores= 0
UNET D2 Theta= 1
UNET D2 Theta Warmup= 1
UNET D2 Z Tol= 0.01
UNET D2 Volume Tol= 0.01
UNET D2 Max Iterations= 20
UNET D2 Equation= 0
UNET D2 RampUpFraction=0.1
UNET D2 TimeSlices= 1
UNET D2 Turbulence Formulation=Non-Conservative (original)
UNET D2 Eddy Viscosity=0.3
UNET D2 Transverse Eddy Viscosity=0.1
UNET D2 Smagorinsky Mixing=0
UNET D2 BCVolumeCheck=0
UNET D2 Cores=0
UNET D2 SolverType=PARDISO (Direct)
UNET D2 Minimum Iterations= 2147483647
UNET D2 Maximum Iterations= 2147483647
UNET D2 Restart Number= 10
UNET D2 Relaxation Coeff=1.3
UNET D2 SOR Precondition Iterations= 10
UNET D2 ILUT Maximum Fill= 8
UNET D2 ILUT Tolerance=1E-08
UNET D1D2 MaxIter= 0
UNET D1D2 ZTol=0.01
UNET D1D2 QTol=0.1
UNET D1D2 MinQTol=1
Write IC File= 0
Write IC File at Fixed DateTime=0
Write IC File at Sim End=0
Echo Input=False
Echo Parameters=False
Echo Output=False
Write Detailed= 0
HDF Write Warmup=0
HDF Write Time Slices=0
HDF Flush=0
HDF Compression= 1
HDF Chunk Size= 1
HDF Spatial Parts= 1
HDF Use Max Rows=0
HDF Fixed Rows= 1
Calibration Method= 0
Calibration Iterations= 20
Calibration Max Change=0.05
Calibration Tolerance=0.2
Calibration Maximum=1.5
Calibration Minimum=0.5
Calibration Optimization Method= 1
WQ AD Non Conservative
WQ ULTIMATE=-1
WQ Max Comp Step=1HOUR
WQ Output Interval=15MIN
WQ Output Selected Increments= 0
WQ Output face flow=0
WQ Output face velocity=0
WQ Output face area=0
WQ Output face dispersion=0
WQ Output cell volume=0
WQ Output cell surface area=0
WQ Output cell continuity=0
WQ Output cumulative cell continuity=0
WQ Output face conc=0
WQ Output face dconc_dx=0
WQ Output face courant=0
WQ Output face peclet=0
WQ Output face adv mass=0
WQ Output face disp mass=0
WQ Output cell mass=0
WQ Output cell source sink temp=0
WQ Output nsm pathways=0
WQ Output nsm derived pathways=0
WQ Create Restart=0
WQ Fixed Restart=0
WQ System Summary=0
WQ Write To DSS=0
Sorting and Armoring Iterations= 10
XS Update Threshold= 0.02
Bed Roughness Predictor= 0
Hydraulics Update Threshold= 0.02
Energy Slope Method= 1
Volume Change Method= 1
Sediment Retention Method= 0
Sediment TS Multiplier= 1
Warm Up Method= 0
XS Weighting Method= 0
Number of US Weighted Cross Sections= 1
Number of DS Weighted Cross Sections= 1
Upstream XS Weight=0
Main XS Weight=1
Downstream XS Weight=0
Number of DS XS's Weighted with US Boundary= 1
Upstream Boundary Weight= 1
Weight of XSs Associated with US Boundary= 0
Number of US XS's Weighted with DS Boundary= 1
Downstream Boundary Weight= 0.5
Weight of XSs Associated with DS Boundary= 0.5
Percentile Method= 0
Sediment Output Level= 3
Mass or Volume Output= 0
Output Increment Type= 1
Profile and TS Output Increment= 1
Transport Output Increment 1
XS Output Flag= 0
XS Output Increment= 10
Read HDF5 Sediment Hotstart= 0
Sediment Hotstart Type= 0
Write Gradation File= 0
Read Gradation Hotstart= 0
Write HDF5 File= 1
Write Binary Output= 1
Write DSS Sediment File= 0
DSS Sediment Output Type= 1
SV Curve= 0
Specific Gage Flag= 0
Subcell Erosion Methods= 0
Subcell Deposition Methods= 0
Advection Scheme= 1
Matrix Solver= 0
Implicit Weighting Factor= 1
Maximum Outer Loop Convergence Iterations= 5
Convergence Maximum Absolute= 0.001
Convergence RMSE= 0.0001
Grain Fractions Max Abs Error= 0.001
Max Subgrid Regions= 1
Max Subgrid Length Scale= 3.402823E+38
Initial Layer Thickness= 3.402823E+38
Min Layer Thickness= 3.402823E+38
Max Layer Thickness= 3.402823E+38
Number of Layers= 5

--- TCKRFRK.f01 (steady flow) ---

Flow Title=Flow
Program Version=6.10
Number of Profiles= 6
Profile Names=01pct,10pct,04pct,02pct,0_2pct,01plus
River Rch & RM=TCKRFRK,Main            ,2961
     613     325     431     519     855     906
Boundary for River Rch & Prof#=TCKRFRK,Main            , 1
Up Type= 0
Dn Type= 3
Dn Slope=0.0407
Boundary for River Rch & Prof#=TCKRFRK,Main            , 2
Up Type= 0
Dn Type= 3
Dn Slope=0.0407
Boundary for River Rch & Prof#=TCKRFRK,Main            , 3
Up Type= 0
Dn Type= 3
Dn Slope=0.0407
Boundary for River Rch & Prof#=TCKRFRK,Main            , 4
Up Type= 0
Dn Type= 3
Dn Slope=0.0407
Boundary for River Rch & Prof#=TCKRFRK,Main            , 5
Up Type= 0
Dn Type= 3
Dn Slope=0.0407
Boundary for River Rch & Prof#=TCKRFRK,Main            , 6
Up Type= 0
Dn Type= 3
Dn Slope=0.0407
DSS Import GetInterval= 0
DSS Import GetPeak= 0
DSS Import FillOption= 0

--- TCKRFRK.g01 (geometry) ---

Geom Title=Geometry
Program Version=6.10

River Reach=TCKRFRK         ,Main
Reach XY= 30
     2328498.669519679.695298611     2328459.832519717.382298611
2328358.79685979519670.8583061382328290.74762767519662.679316272
2328222.59786336519675.0676093552328126.08449232519648.322125061
2328009.10054844519669.839662965 2327947.5561169519659.591528986
2327824.63629131 519680.98173385      2327628.55519877.572298611
     2327605.839519932.762298611     2327575.951519962.556298611
2327412.39779376520000.848618109      2327320.15519984.216298611
     2327270.483520009.3642986112327238.53983082520046.695155087
     2327190.894520149.8152986112327130.41065085520208.294676526
2327101.13517965520220.5562032512326970.95476325520211.982771885
2326948.39229752 520220.660643322326853.46030912 520326.35064592
2326725.53118104520430.652197238     2326668.035520533.397298611
2326538.15652476520601.126394326     2326506.204520755.624298611
2326456.37892975 520873.744964742326420.91273406520886.642829105
2326300.68489941520895.1836461182326230.99705455520941.862049639

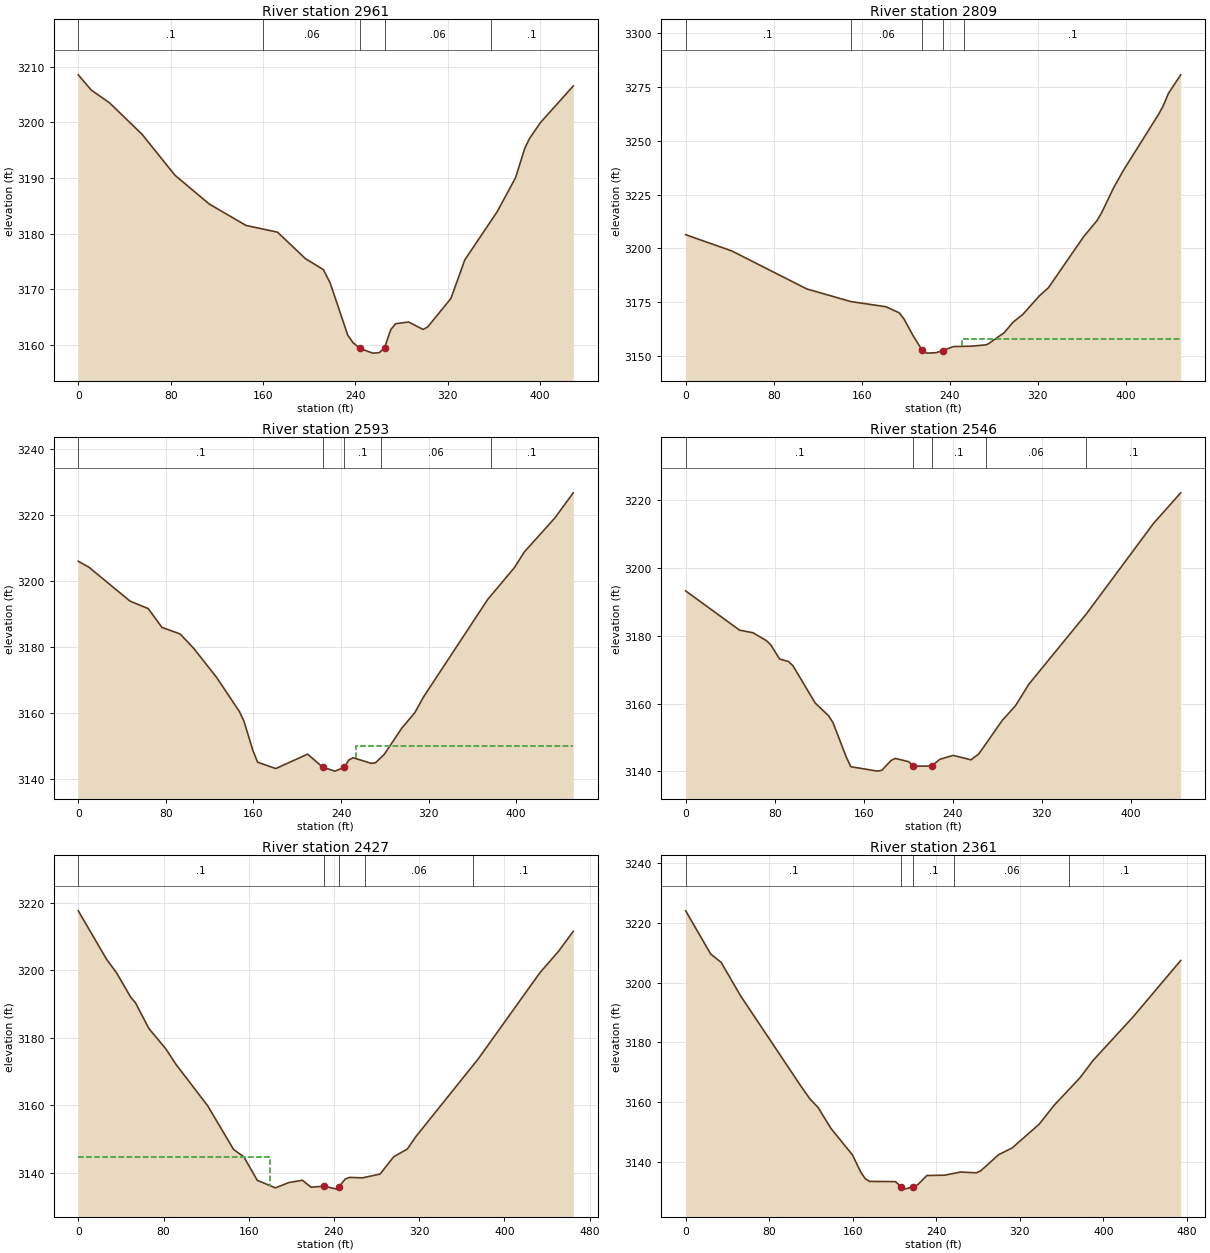
Type RM Length L Ch R = 1 ,2961    ,151.7,151.7,151.7
XS GIS Cut Line= 4
2328438.21221634519446.4008363162328469.01098295519657.512382017
2328525.00874043519706.2304310242328666.12308929519711.830206772
#Sta/Elev= 30
       0 3208.55    11.2 3205.82    27.1 3203.51    55.4 3197.83    83.7 3190.52
   113.5 3185.33   145.3 3181.49   172.6 3180.28   196.8 3175.52   212.3 3173.56
   218.2 3171.16   233.4  3161.8     238 3160.43     244 3159.39     255 3158.55
   260.7 3158.63   265.3 3159.47   270.6 3162.74   274.9 3163.84   286.2 3164.14
   298.7  3162.8   302.7 3163.26   322.8 3168.37   334.8 3175.29   362.8 3183.93
   378.8 3190.06   386.8 3195.34   390.8 3197.08   400.3 3199.95   428.8 3206.55
#Mann= 5 ,-1,0
       0      .1       0     160     .06       0     244    .045       0
   265.3     .06       0  357.57      .1       0
Bank Sta=244,265.3
XS Rating Curve= 0 ,0
Exp/Cntr=0.3,0.1

Type RM Length L Ch R = 1 ,2809    ,216.2,216.2,216.2
XS GIS Cut Line= 4
 2328378.3889862519451.2281531722328381.36744485 519644.38507573
2328357.46960596519727.1740175932328344.06599407519896.960182759
#Sta/Elev= 30
       0 3206.35      42 3198.78     110 3181.15     150 3175.28     182 3172.86
     194 3170.03   198.2 3167.33   206.5 3159.52   214.8 3152.69     219 3151.31
   227.3  3151.5   233.6  3152.5   243.2 3154.35   260.6 3154.57   273.1 3155.18
   275.6 3155.86   289.4 3160.82   297.4 3165.68   306.3 3169.32   321.5    3178
   329.5 3181.66   361.6 3205.46   373.6 3212.84   377.7 3216.36     389 3228.37
   397.7 3236.24   429.8 3262.45   433.8  3266.2   438.6 3272.01   449.7 3280.65
#Mann= 5 ,-1,0
       0      .1       0     150     .06       0   214.8    .045       0
   233.6     .06       0  253.18      .1       0
#XS Ineff= 2 , 0
                          250.97         3157.86
Permanent Ineff=
       F       F
Bank Sta=214.8,233.6
XS Rating Curve= 0 ,0
Exp/Cntr=0.3,0.1

Type RM Length L Ch R = 1 ,2593    ,47.1,47.1,47.1
XS GIS Cut Line= 3
2328226.98812803519431.7882207482328156.14810561519678.448057843
2328160.41557684519873.898240179
#Sta/Elev= 30
       0 3205.98     9.8 3204.15    47.2 3193.89    63.9  3191.6    76.4 3185.91
      93 3183.91   105.5 3179.52   126.4  3170.7   147.1  3160.4   151.3 3157.46
   159.6 3148.44   163.8 3144.99   180.4 3143.06   209.5 3147.44   223.3 3143.46
   234.5 3142.28   243.1 3143.45     247 3145.63   251.1 3146.35   267.4 3144.65
   271.4  3144.8   279.4 3147.34   295.4 3155.29   307.4 3160.03   315.4 3164.83
   373.9 3194.36   398.5 3204.11   407.4 3208.79   435.3 3219.12   452.1 3226.74
#Mann= 5 ,-1,0
       0      .1       0   223.3    .045       0   243.1      .1       0
  276.63     .06       0  376.63      .1       0
#XS Ineff= 2 , 0
                          253.24         3150.04
Permanent Ineff=
       F       F
Bank Sta=223.3,243.1
XS Rating Curve= 0 ,0
Exp/Cntr=0.3,0.1

Type RM Length L Ch R = 1 ,2546    ,118.6,118.6,118.6
XS GIS Cut Line= 2
2328114.36453831519436.7899979572328119.02996165519881.560356209
#Sta/Elev= 30
       0 3193.25    48.4 3181.67    60.4 3180.91    72.4 3178.61    76.4 3177.36
    84.4 3173.15    92.4 3172.41    96.4 3171.15   116.4 3160.15   128.4 3156.41
   132.4 3154.36   144.4 3144.13   148.4 3141.36   172.4 3140.06   176.4 3140.34
   184.5 3143.18   188.4 3143.82   200.4 3142.84   204.7 3141.54   220.9 3141.56
   228.4 3143.56   240.4 3144.71   256.4  3143.4   263.5 3145.17   284.4 3155.01
   296.4 3159.38   308.4 3165.73   360.4 3186.62   420.4 3213.18   444.8  3222.2
#Mann= 5 ,-1,0
       0      .1       0   204.7    .045       0   220.9      .1       0
     270     .06       0     360      .1       0
Bank Sta=204.7,220.9
XS Rating Curve= 0 ,0
Exp/Cntr=0.3,0.1

Type RM Length L Ch R = 1 ,2427    ,65.9,65.9,65.9
XS GIS Cut Line= 4
2327928.78436552519446.6392250052327998.24733522519643.623765955
2328004.46789967519705.3110300952328062.00812084519890.372822515
#Sta/Elev= 30
       0 3217.54    26.6 3203.17      36 3199.14    49.3 3191.91    53.6 3190.34
    66.3 3182.68    82.4 3176.57    91.8 3172.02   121.5 3159.78   145.8 3146.85
   155.4 3144.67   168.1  3137.7   185.1 3135.48   197.8 3137.06   210.4 3137.73
   218.5 3135.67   230.8 3135.97   242.6  3135.1   244.9 3135.83   250.6  3138.1
   254.7 3138.58   266.8 3138.44   283.3 3139.56   296.1 3144.68   308.9 3146.98
   316.8  3150.6   375.5 3173.69   433.5 3199.25   450.9 3205.56   464.7 3211.47
#Mann= 5 ,-1,0
       0      .1       0   230.8    .045       0   244.9      .1       0
  268.87     .06       0  370.87      .1       0
#XS Ineff= 2 , 0
             180 3144.56
Permanent Ineff=
       F       F
Bank Sta=230.8,244.9
XS Rating Curve= 0 ,0
Exp/Cntr=0.3,0.1

Type RM Length L Ch R = 1 ,2361    ,102.6,102.6,102.6
XS GIS Cut Line= 3
2327884.35477855519453.8207774422327929.86880401519645.679900129
2328031.40009156519903.359305782
#Sta/Elev= 30
       0 3223.93      24 3209.49    33.9 3206.76    52.8 3195.44   110.3 3165.45
   118.9 3161.18   126.8  3158.3   139.1 3151.31   159.7 3142.47   167.9 3136.58
     172 3134.52   176.1 3133.61   200.9 3133.54   206.4 3131.84   209.5 3131.03
   218.1 3131.78   222.4 3132.56     231 3135.57   248.2 3135.69   263.3 3136.74
   278.3 3136.48   282.6 3137.15   299.8 3142.54   312.7 3144.78   338.5 3152.68
   352.8 3158.98   377.5 3168.14   390.1 3173.95   428.8 3188.63   474.1 3207.34
#Mann= 5 ,-1,0
       0      .1       0   206.4    .045       0   218.1      .1       0
  257.18     .06       0  367.18      .1       0
Bank Sta=206.4,218.1
XS Rating Curve= 0 ,0
Exp/Cntr=0.3,0.1

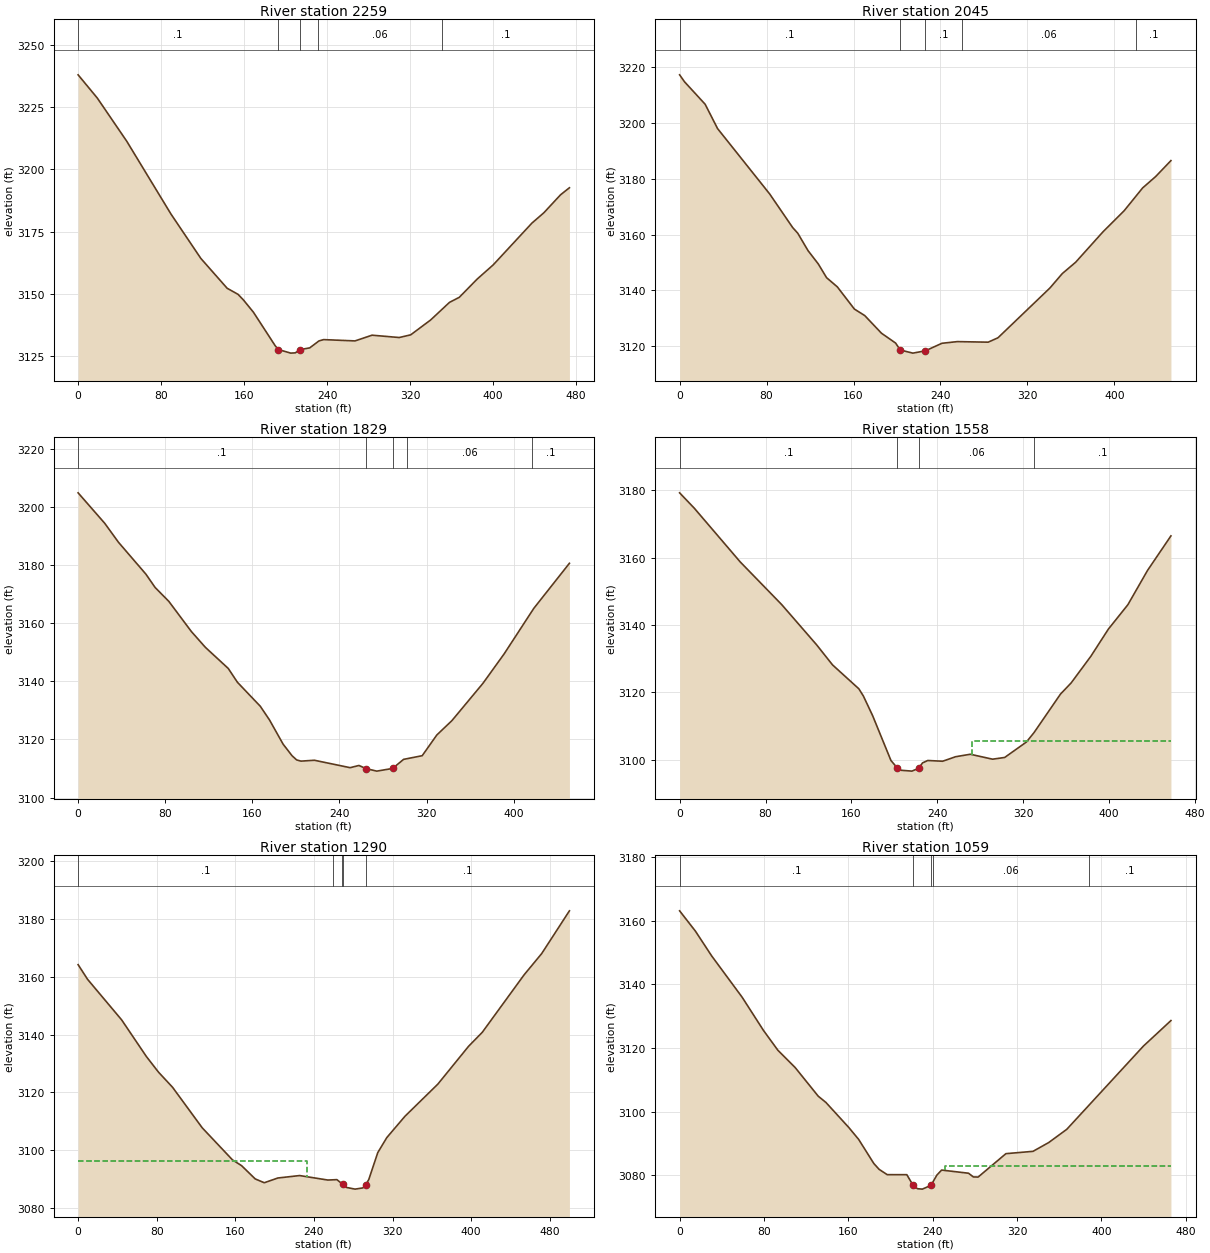
Type RM Length L Ch R = 1 ,2259    ,214.4,214.4,214.4
XS GIS Cut Line= 4
2327712.05512263519515.1729939022327821.76481919 519645.69062487
2327842.39673519 519691.772337822327972.97794987 519908.16427585
#Sta/Elev= 30
       0 3237.97    18.5 3228.64    46.9 3211.28    89.5 3182.04   118.3  3164.2
   143.7 3152.19   154.2 3149.75   159.4 3147.49     169 3142.58   190.1 3129.04
   193.1 3127.57     205 3126.12   209.4 3126.23  213.89 3127.51   223.3 3128.23
   232.2 3131.02   236.7 3131.55     267 3131.03   283.4 3133.33   309.6 3132.39
   320.7 3133.48   339.9 3139.45   358.1 3146.53   367.5 3148.55   384.8  3155.9
   400.2 3161.58   437.5 3178.36     449 3182.51   465.1 3189.74   473.7 3192.58
#Mann= 5 ,-1,0
       0      .1       0   193.1    .045       0  213.89      .1       0
  230.99     .06       0  350.99      .1       0
Bank Sta=193.1,213.89
XS Rating Curve= 0 ,0
Exp/Cntr=0.3,0.1

Type RM Length L Ch R = 1 ,2045    ,215.7,215.7,215.7
XS GIS Cut Line= 2
 2327567.8484572519641.3354750632327809.65940075520023.236319525
#Sta/Elev= 30
       0 3217.33     4.5 3214.84    23.5 3206.77    34.9 3198.06    82.9 3174.58
     104 3162.56   108.7 3160.52   118.2 3154.24   127.5 3149.55   135.2 3144.58
   145.1 3141.28   160.8 3133.32   170.3 3130.99   185.7 3124.66   198.7 3121.13
     203 3118.63   214.6 3117.52   226.2 3118.36   241.3 3121.05   255.5 3121.65
   283.9 3121.45   292.9 3123.03   340.7 3140.89     352 3146.03   364.4 3150.14
   389.4 3160.99   408.9 3168.56   425.9 3176.74   437.9 3180.83     452 3186.56
#Mann= 5 ,-1,0
       0      .1       0     203    .045       0   226.2      .1       0
     260     .06       0     420      .1       0
Bank Sta=203,226.2
XS Rating Curve= 0 ,0
Exp/Cntr=0.3,0.1

Type RM Length L Ch R = 1 ,1829    ,270.7,270.7,270.7
XS GIS Cut Line= 4
2327464.62434169 519705.895215512327523.32296813 519888.97213356
 2327547.3788615520000.5164556362327611.15632219520130.538611872
#Sta/Elev= 30
       0 3204.89    24.5 3194.38    37.1 3187.86    62.3 3176.88    70.7 3172.32
    83.3 3167.54     104 3157.16   116.9  3151.7   137.9 3144.44   146.3 3139.69
   167.3 3131.43   175.7 3126.76   188.3 3118.36   196.5 3114.39   200.7 3112.96
   204.7 3112.54     217 3112.84   249.8 3110.29   257.9 3111.05   264.5 3109.96
   274.3  3109.1   288.83110.022   298.9 3113.15     316 3114.41   329.4 3121.53
   343.3 3126.49   371.8 3139.33   391.2 3149.43   418.5 3165.13   451.2 3180.64
#Mann= 5 ,-1,0
       0      .1       0   264.5    .045       0   288.8      .1       0
  302.26     .06       0  416.37      .1       0
Bank Sta=264.5,288.8
XS Rating Curve= 0 ,0
Exp/Cntr=0.3,0.1

Type RM Length L Ch R = 1 ,1558    ,268.1,268.1,268.1
XS GIS Cut Line= 2
2327156.33448715519830.0955844132327424.98960811520200.379233713
#Sta/Elev= 30
       0 3179.17    13.7  3174.6    56.5 3158.67    95.1 3146.03   127.4 3134.19
   142.4 3128.17   166.9 3121.09   171.1 3118.96   179.7 3113.15   196.8 3099.83
   202.6 3097.67   206.4 3096.94   216.3 3096.69   222.6 3097.54   226.2 3099.13
   231.1 3099.84   244.9 3099.62     257 3100.96   270.7 3101.69   291.4 3100.23
   302.7 3100.74   322.9 3105.31     330  3108.1   354.7 3119.54   364.6 3122.84
     383 3130.76   399.2 3138.76   417.4 3146.01   435.7 3156.17   457.5 3166.41
#Mann= 4 ,-1,0
       0      .1       0   202.6    .045       0   222.6     .06       0
     330      .1       0
#XS Ineff= 2 , 0
                          272.11         3105.76
Permanent Ineff=
       F       F
Bank Sta=202.6,222.6
XS Rating Curve= 0 ,0
Exp/Cntr=0.3,0.1

Type RM Length L Ch R = 1 ,1290    ,230.9,230.9,230.9
XS GIS Cut Line= 3
2327002.61231875 519960.172698662327058.68266049520098.069330631
2327234.30268408520402.020674024
#Sta/Elev= 30
       0 3164.19     9.7 3159.09    44.3  3145.1    69.5 3132.42    81.8 3127.03
    96.1  3121.8   126.3 3107.78   157.1 3096.69   166.3 3094.71   180.2 3090.12
   189.4  3088.8   203.3 3090.44   225.4 3091.28   254.1 3089.73   263.3 3089.87
   269.3 3088.25   272.6 3087.21   281.8 3086.59   289.8 3087.02   292.8 3088.15
   295.8 3089.95   304.9 3099.21   314.1 3104.41   332.6 3111.79     366 3122.88
   397.3 3135.97   411.2 3140.79   453.8 3160.68   471.7 3168.03   499.9  3182.8
#Mann= 5 ,-1,0
       0      .1       0  258.86     .06       0  268.86      .1       0
   269.3    .045       0   292.8      .1       0
#XS Ineff= 2 , 0
          233.24 3096.38
Permanent Ineff=
       F       F
Bank Sta=269.3,292.8
XS Rating Curve= 0 ,0
Exp/Cntr=0.3,0.1

Type RM Length L Ch R = 1 ,1059    ,159.1,159.1,159.1
XS GIS Cut Line= 5
2326779.95590317520075.3027753952326890.08482622520242.673850531
2326939.23841334520270.050531966 2326969.7260813520323.559500225
2327073.63303129520428.710844828
#Sta/Elev= 30
       0 3163.15      15 3156.76    30.4 3148.98    59.3 3135.99    79.5 3125.57
    93.2 3119.32   109.6 3113.88   131.5 3104.87   138.7 3102.93   160.3  3095.1
   169.8  3091.3   184.2 3083.72   189.2 3081.88   196.9 3080.21   215.5  3080.2
   221.4 3076.89   225.6 3075.79   230.2 3075.66   238.4 3076.84     244 3080.07
   248.5 3081.65     274 3080.66   278.6  3079.5   283.1 3079.45   309.5 3086.81
   335.2 3087.54   350.1 3090.31   367.2 3094.46   439.9 3120.63     466 3128.65
#Mann= 5 ,-1,0
       0      .1       0   221.4    .045       0   238.4      .1       0
  240.35     .06       0   388.2      .1       0
#XS Ineff= 2 , 0
                          251.64         3082.84
Permanent Ineff=
       F       F
Bank Sta=221.4,238.4
XS Rating Curve= 0 ,0
Exp/Cntr=0.3,0.1

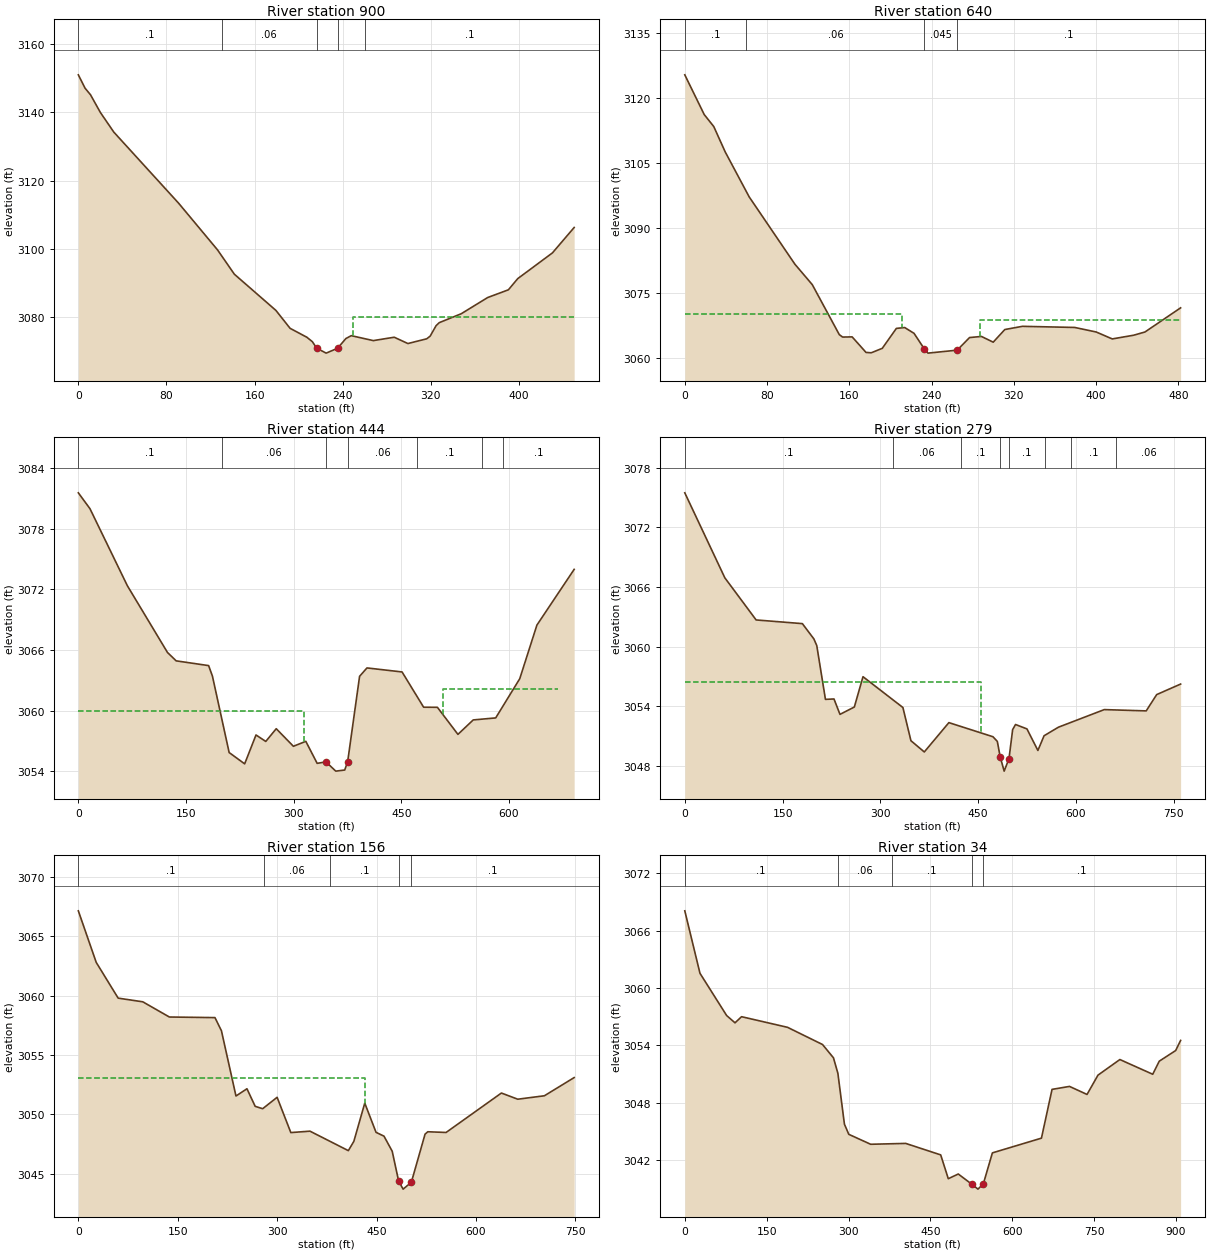
Type RM Length L Ch R = 1 ,900     ,260.4,260.4,260.4
XS GIS Cut Line= 2
2326664.42065013520189.3403891532326940.27586618520544.873650295
#Sta/Elev= 30
       0 3151.03     6.1 3147.12    11.1 3145.16      20    3140    32.2 3134.24
      91  3113.4   126.4 3099.68   141.6 3092.58   179.3 3081.97   192.2 3076.71
   207.4  3074.1   212.4 3072.79   216.4 3070.88   224.9 3069.44  235.273070.857
   242.8 3073.71   247.7 3074.56   267.7 3073.11   286.7  3074.1   299.1 3072.25
   316.2 3073.64   319.3 3074.42   324.7 3077.49   327.6 3078.38   347.5 3080.98
   371.5 3085.74   390.3    3088   398.8 3091.28   430.3 3098.83     450 3106.27
#Mann= 5 ,-1,0
       0      .1       0     130     .06       0   216.4    .045       0
  235.27     .06       0     260      .1       0
#XS Ineff= 2 , 0
                           249.3         3079.98
Permanent Ineff=
       F       F
Bank Sta=216.4,235.27
XS Rating Curve= 0 ,0
Exp/Cntr=0.3,0.1

Type RM Length L Ch R = 1 ,640     ,195.1,195.1,195.1
XS GIS Cut Line= 4
2326506.72601349520336.8742413082326616.72067489520523.758110232
2326648.40533165 520584.956808762326799.17289112520710.990806674
#Sta/Elev= 30
       0 3125.36    18.9 3116.18    28.2 3113.41    39.3 3107.56    62.6 3097.18
   107.1 3081.62     124  3076.9   150.3 3065.35   153.5 3064.79   162.8 3064.83
   176.3 3061.24   181.4 3061.16   192.1 3062.19   205.8 3066.79   213.9 3066.99
     223 3065.65   233.1 3062.01   236.5 3061.08     265 3061.77     277 3064.68
   288.6 3064.93     300 3063.61   311.3 3066.53   328.4 3067.27   379.3 3067.01
   400.2 3065.96   415.8 3064.36   436.7 3065.22   447.6 3065.96   482.3 3071.54
#Mann= 4 ,-1,0
       0      .1       0      60     .06       0   233.1    .045       0
     265      .1       0
#XS Ineff= 2 , 0
          210.99 3070.09  287.32         3068.71
Permanent Ineff=
       F       F
Bank Sta=233.1,265
XS Rating Curve= 0 ,0
Exp/Cntr=0.3,0.1

Type RM Length L Ch R = 1 ,444     ,165.3,165.3,165.3
XS GIS Cut Line= 4
2326317.87730836520401.0455991212326499.24404095520680.021316012
2326566.14323809520698.4188586482326807.63841687520856.418646202
#Sta/Elev= 30
       0 3081.56    16.2 3079.99    68.3 3072.36   124.2 3065.75   136.3 3064.92
   181.5 3064.45   186.8 3063.41   210.1 3055.84   231.7 3054.72   247.5 3057.58
   261.1 3056.94   275.7  3058.2   299.6 3056.46   316.9 3056.95   332.7 3054.77
  344.993054.915   358.6    3054   371.1 3054.11   375.2 3054.94   391.8 3063.39
   402.1 3064.22     451 3063.82     481 3060.33   500.2 3060.32   528.8 3057.64
   550.1 3059.07   581.4 3059.27   614.9 3063.15   638.8 3068.46   690.7 3073.98
#Mann= 7 ,-1,0
       0      .1       0     200     .06       0  344.99    .045       0
   375.2     .06       0  472.13      .1       0  562.13     .06       0
  592.13      .1       0
#XS Ineff= 2 ,-1
       0   314.7 3059.93  508.34   668.6 3062.15
Permanent Ineff=
       F       F
Bank Sta=344.99,375.2
XS Rating Curve= 0 ,0
Exp/Cntr=0.3,0.1

Type RM Length L Ch R = 1 ,279     ,123.1,123.1,123.1
XS GIS Cut Line= 6
2326277.77354473520398.4305759682326416.73094292520690.171979138
2326450.60612954520833.9686897062326488.43006565520849.468428951
2326652.09023216520923.8696090082326703.88918538520969.289986196
#Sta/Elev= 30
       0 3075.47    61.4 3066.92   109.4 3062.68   180.3 3062.31     198 3060.77
   202.4  3060.1   215.7 3054.69   228.8 3054.73     238 3053.18     260 3053.92
   273.3 3056.97   334.5 3053.87   346.8 3050.53   367.3  3049.4     405 3052.35
   472.6 3050.93   479.3 3050.46   483.7  3048.9   489.8 3047.47   497.2 3048.73
   502.8 3051.65   507.2 3052.16   524.7 3051.72   541.5 3049.55     551 3051.03
     573 3051.89   643.3 3053.66   707.6 3053.53   723.7 3055.17   760.4 3056.23
#Mann= 8 ,-1,0
       0      .1       0     320     .06       0  423.14      .1       0
   483.7    .045       0   497.2      .1       0  551.75     .06       0
  591.75      .1       0  661.75     .06       0
#XS Ineff= 2 , 0
          454.76 3056.39
Permanent Ineff=
       F       F
Bank Sta=483.7,497.2
XS Rating Curve= 0 ,0
Exp/Cntr=0.3,0.1

Type RM Length L Ch R = 1 ,156     ,121.8,121.8,121.8
XS GIS Cut Line= 4
2326246.54337382520415.0352355812326380.66145641520925.928344007
2326400.42338024520944.0551769262326592.89986546 520926.61967433
#Sta/Elev= 30
       0 3067.13      27 3062.79    60.1 3059.78    97.3 3059.47   137.4 3058.19
   206.2 3058.14     216 3057.03   237.9 3051.54   254.5 3052.15   266.9 3050.67
   278.2 3050.47     300 3051.43   320.7 3048.46   349.6 3048.58   407.5 3046.94
   415.8 3047.72   432.3 3050.94   449.3 3048.48   461.3 3048.16   473.7 3046.89
   483.53044.358   490.2  3043.7   502.6 3044.28   523.3 3048.33   527.4 3048.53
     555 3048.47   638.5 3051.79   663.2 3051.27   703.4 3051.56   748.3 3053.09
#Mann= 5 ,-1,0
       0      .1       0     280     .06       0     380      .1       0
   483.5    .045       0   502.6      .1       0
#XS Ineff= 2 , 0
          433.13 3053.07
Permanent Ineff=
       F       F
Bank Sta=483.5,502.6
XS Rating Curve= 0 ,0
Exp/Cntr(USF)=0,0
Exp/Cntr=0.3,0.1

Type RM Length L Ch R = 1 ,34      ,,,
XS GIS Cut Line= 4
2326234.39262191520405.412725565 2326200.2470167520887.011309661
2326348.98161248520970.809646699 2326603.1618806520950.335294698
#Sta/Elev= 30
       0 3068.06    27.8 3061.53    76.7 3057.11      92 3056.35     104 3056.99
   188.2 3055.88   252.4 3054.08   272.4 3052.69   280.5 3051.07   292.5 3045.75
   300.5 3044.69   340.6 3043.65   404.8 3043.74   468.9 3042.54   482.8 3040.05
   501.1 3040.54   525.5 3039.49   537.2 3038.96     547 3039.51   563.6 3042.75
   653.5 3044.29   672.9 3049.39   704.9  3049.7     737 3048.86   757.1 3050.88
   797.2 3052.51   857.4 3050.97   869.4 3052.34   899.4 3053.45   908.5 3054.51
#Mann= 5 ,-1,0
       0      .1       0     280     .06       0     380      .1       0
   525.5    .045       0     547      .1       0
Bank Sta=525.5,547
XS Rating Curve= 0 ,0
Exp/Cntr=0.3,0.1
LCMann Table=0

Chan Stop Cuts=-1
Use User Specified Reach Order=0
Composite Channel Slope=5